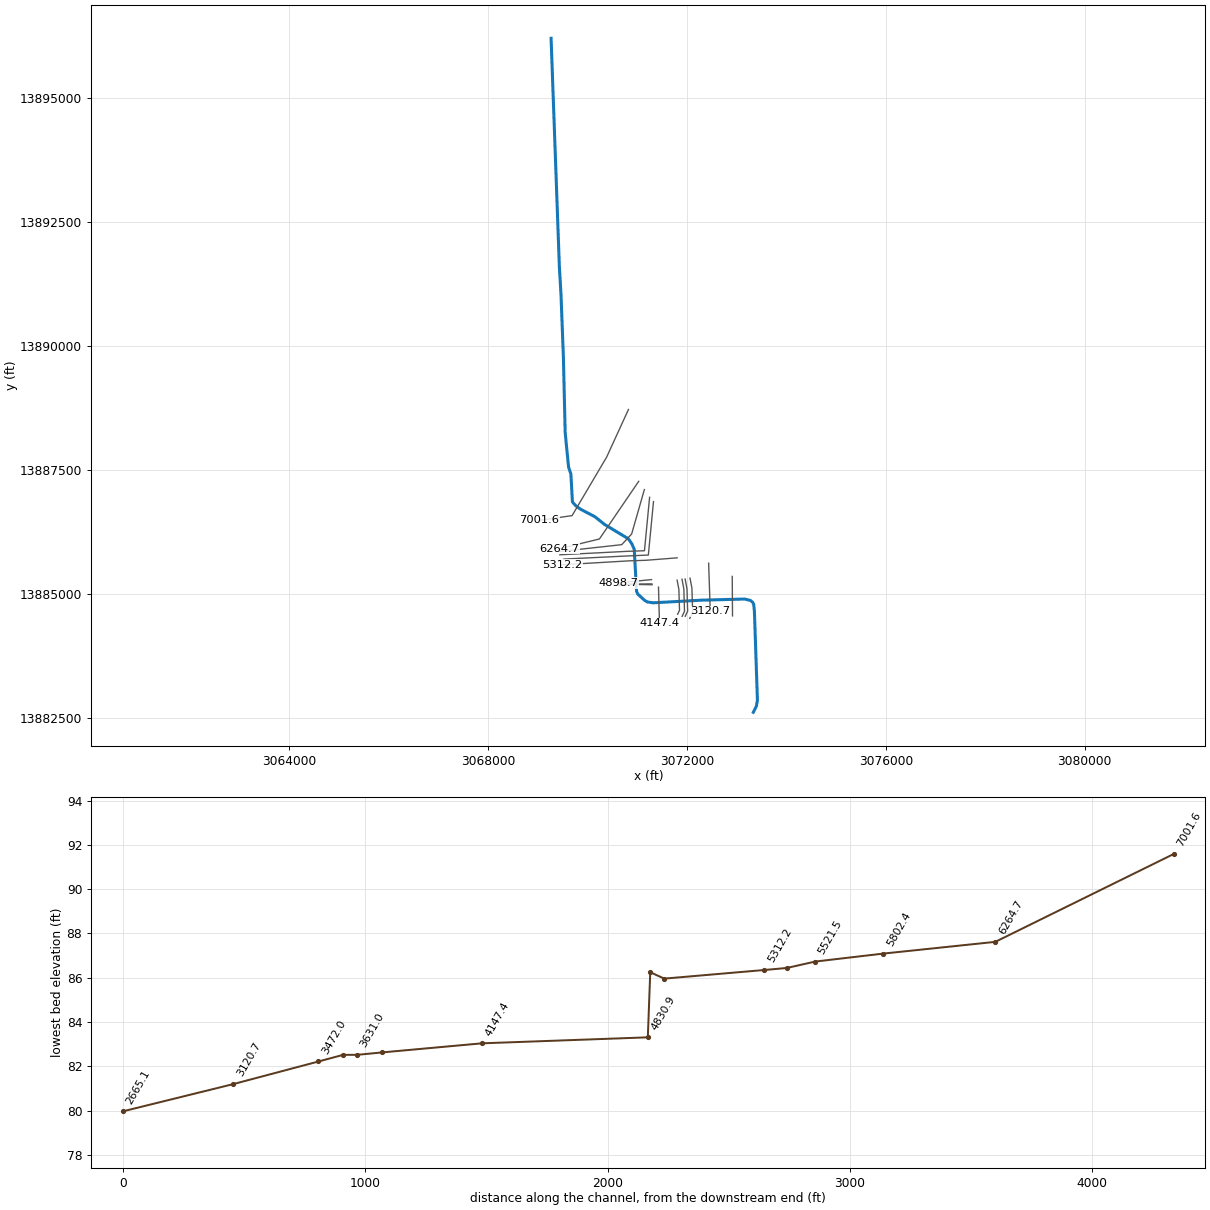
--- E124-00-00.prj (project) ---

Proj Title=E124-00-00
Current Plan=p02
Default Exp/Contr=.3,.1
English Units
Geom File=g01
Flow File=f01
Flow File=f04
Flow File=f02
Plan File=p01
Plan File=p04
Plan File=p02
Y Axis Title=Elevation
X Axis Title(PF)=Main Channel Distance
X Axis Title(XS)=Station
BEGIN DESCRIPTION:
White Oak Bayou Watershed
WOB Trib 15.8
HCFCD Unit E124-00-00
Flood Hazard Model
10, 2, 1, 0.2%
Filename E124-00-00
Prepared by:  Sabine Borgnet-Harris  DATE:  March 25, 2004
Reviewed by:  _____________________  DATE:  __________________
STATUS (Final)
END DESCRIPTION:
DSS File=dss
DSS Export Rating Curves= 0
DSS Export Rating Curve Sorted= 0
DSS Export Volume Flow Curves= 0
DXF OffsetX= 0
DXF OffsetY= 0
DXF ScaleX= 1
DXF ScaleY= 10

--- E124-00-00.p02 (plan) ---

Plan Title=Floodway
Version=Version 3.0.1  Mar 2001
Short Identifier=Floodway0607
Geom File=g01
Flow File=f02
Subcritical Flow
K Sum by GR= 0
Std Step Tol= 0.01
Critical Tol= 0.01
Num of Std Step Trials= 40
Max Error Tol= 0.3
Flow Tol Ratio= 0.001
Split Flow NTrial= 30
Split Flow Tol= 0.02
Split Flow Ratio= 0.02
Log Output Level= 0
Friction Slope Method= 1
Unsteady Friction Slope Method= 2
Parabolic Critical Depth
Global Vel Dist= 0 , 0 , 0
Global Log Level= 0
CheckData=True
Encroach Param=-1 ,,, 5
Encroach River=E124-00-00
Encroach Reach=Reach - 1
Encroach Node=7001.6
       1  4952.3  5041.9       1    4932    5062       1    4932    5062
       1    4932    5062
Encroach Node=6264.7
       1  4954.9  5039.4       1    4935    5060       1    4935    5060
       1    4935    5060
Encroach Node=5802.4
       1 4920.52  5080.7       0       0       0       0       0       0
       0       0       0
Encroach Node=5521.5
       1  4897.1    5043       1  4897.1    5043       1  4897.1    5043
       1  4897.1    5043
Encroach Node=5445.7
       1  4897.1    5043       1  4897.1    5043       1  4897.1    5043
       1  4897.1    5043
Encroach Node=5404.0
       1  4950.5    5040       1  4950.5    5040       1  4950.5    5040
       1  4950.5    5040
Encroach Node=5312.2
       1 4961.55  5053.7       0       0       0       0       0       0
       0       0       0
Encroach Node=4898.7
       1  4960.8  5035.6       1  4960.8  5035.6       1  4960.8  5035.6
       1  4960.8  5035.6
Encroach Node=4840.9
       1    4972  5032.1       1    4972  5032.1       1    4972  5032.1
       1    4972  5032.1
Encroach Node=4830.9
       1  4968.9    5031       1  4968.9    5031       1  4968.9    5031
       1  4968.9    5031
Encroach Node=4147.4
       1  4951.2  5041.6       1  4951.2  5041.6       1  4951.2  5041.6
       1  4951.2  5041.6
Encroach Node=3735.5
       1 4961.65    5058       0       0       0       0       0       0
       0       0       0
Encroach Node=3631.0
       1  4964.3  5038.8       1  4964.3  5038.8       1  4964.3  5038.8
       1  4964.3  5038.8
Encroach Node=3602.5
       1  4964.3  5038.8       1  4964.3  5038.8       1  4964.3  5038.8
       1  4964.3  5038.8
Encroach Node=3574.0
       1  4964.3  5038.8       1  4964.3  5038.8       1  4964.3  5038.8
       1  4964.3  5038.8
Encroach Node=3472.0
       1 4961.98 5040.42       0       0       0       0       0       0
       0       0       0
Encroach Node=3120.7
       1    4954    5046       1    4954    5046       1    4954    5046
       1    4954    5046
Encroach Node=2665.1
       1 4961.16 5039.43       0       0       0       0       0       0
       0       0       0
Encroach Node=2579.6
       1  4962.5  5038.2       1  4962.5  5038.2       1  4962.5  5038.2
       1  4962.5  5038.2
Encroach Node=2567.3
       1    4962  5038.2       1    4962  5038.2       1    4962  5038.2
       1    4962  5038.2
Encroach Node=2556.8
       1    4962  5038.3       1    4962  5038.3       1    4962  5038.3
       1    4962  5038.3
Encroach Node=2546.3
       1    4962  5038.3       1    4962  5038.3       1    4962  5038.3
       1    4962  5038.3
Encroach Node=2438.7
       1  4959.6 5039.72       0       0       0       0       0       0
       0       0       0
Encroach Node=1895.1
       1  4947.5  5046.9       1  4947.5  5046.9       1  4947.5  5046.9
       1  4947.5  5046.9
Encroach Node=1278.3
       1  4945.2  5053.6       1  4945.2  5053.6       1  4945.2  5053.6
       1  4945.2  5053.6
Encroach Node=636.0
       1  4945.7  5052.3       1  4945.7  5052.3       1  4945.7  5052.3
       1  4945.7  5052.3
Encroach Reach=E124-00-00_0006
Encroach Node=7001.6
       1  4952.3  5041.9       0       0       0       0       0       0
       0       0       0
Encroach Node=6264.7
       1  4954.9  5039.4       0       0       0       0       0       0
       0       0       0
Encroach Node=5802.4
       1 4920.52  5080.7       0       0       0       0       0       0
       0       0       0
Encroach Node=5521.5
       1  4897.1    5043       0       0       0       0       0       0
       0       0       0
Encroach Node=5445.7
       1  4897.1    5043       0       0       0       0       0       0
       0       0       0
Encroach Node=5404.0
       1  4950.5    5040       0       0       0       0       0       0
       0       0       0
Encroach Node=5312.2
       1 4961.55  5053.7       0       0       0       0       0       0
       0       0       0
Encroach Node=4898.7
       1  4960.8  5035.6       0       0       0       0       0       0
       0       0       0
Encroach Node=4840.9
       1    4972  5032.1       0       0       0       0       0       0
       0       0       0
Encroach Node=4830.9
       1  4968.9    5031       0       0       0       0       0       0
       0       0       0
Encroach Node=4147.4
       1  4951.2  5041.6       0       0       0       0       0       0
       0       0       0
Encroach Node=3735.5
       1 4961.65    5058       0       0       0       0       0       0
       0       0       0
Encroach Node=3631.0
       1  4964.3  5038.8       0       0       0       0       0       0
       0       0       0
Encroach Node=3602.5
       1  4964.3  5038.8       0       0       0       0       0       0
       0       0       0
Encroach Node=3574.0
       1  4964.3  5038.8       0       0       0       0       0       0
       0       0       0
Encroach Node=3472.0
       1 4961.98 5040.42       0       0       0       0       0       0
       0       0       0
Encroach Node=3120.7
       1    4954    5046       0       0       0       0       0       0
       0       0       0
Encroach Node=2665.1
       1 4961.16 5039.43       0       0       0       0       0       0
       0       0       0
Encroach Node=2579.6
       1  4962.5  5038.2       0       0       0       0       0       0
       0       0       0
Encroach Node=2567.3
       1    4962  5038.2       0       0       0       0       0       0
       0       0       0
Encroach Node=2556.8
       1    4962  5038.3       0       0       0       0       0       0
       0       0       0
Encroach Node=2546.3
       1    4962  5038.3       0       0       0       0       0       0
       0       0       0
Encroach Node=2438.7
       1  4959.6 5039.72       0       0       0       0       0       0
       0       0       0
Encroach Node=1895.1
       1  4947.5  5046.9       0       0       0       0       0       0
       0       0       0
Encroach Node=1278.3
       1  4945.2  5053.6       0       0       0       0       0       0
       0       0       0
Encroach Node=636.0
       1  4945.7  5052.3       0       0       0       0       0       0
       0       0       0
Computation Interval=1HOUR
Output Interval=1HOUR
Run HTab= 0
Run UNet= 0
Run PostProcess= 0
UNET Theta= 1
UNET ZTol= 0.02
UNET ZSATol= 0.1
UNET MxIter= 20
UNET MaxInSteps= 20
UNET DtIC= 0
UNET DtMin= 0
UNET MaxCRTS= 20
UNET WFStab= 2
UNET SFStab= 1
UNET WFX= 1
UNET SFX= 1
UNET Convert EG Bridges=-1
UNET Use Existing IB Tables=-1
Instantaneous Interval=1HOUR
DSS File=dss
Write IC File= 0
IC Time=0
Write Velocity= 0
Write Detailed= 0

--- E124-00-00.p01 (plan) ---

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Plan Title=FEMA Effective June 2007
Short Identifier=FEMAeff0607
Geom File=g01
Flow File=f01
Num of Std Step Trials= 20
Encroach Param=-1 ,0,0, 0

--- E124-00-00.p04 (plan) ---

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Plan Title=Storage Routing
Program Version=3.13
Short Identifier=Store_Rout
Geom File=g01
Flow File=f04
Num of Std Step Trials= 20
Unsteady Bridges Friction Slope Method= 1
Encroach Param=-1 ,0,0, 0
UNET Theta Warmup= 1
UNET DSS MLevel= 4
UNET DZMax Abort= 100
UNET Froude Reduction=False
UNET Froude Limit= 1
UNET Froude Power= 10
Echo Input=False
Echo Output=False
Detailed Automatic Start=False, 10

--- E124-00-00.f02 (steady flow) ---

Flow Title=Floodway
Version=Version 3.0.1  Mar 2001
Number of Profiles= 2
Profile Names=1PCT_100yr, 1PCTFloodway_100yrFW
River Rch & RM=E124-00-00,E124-00-00_0006       ,7001.6
    1000    1000
River Rch & RM=E124-00-00,E124-00-00_0006       ,6264.7
    1100    1100
River Rch & RM=E124-00-00,E124-00-00_0006       ,5521.5
    1160    1160
River Rch & RM=E124-00-00,E124-00-00_0006       ,4898.7
    1240    1240
River Rch & RM=E124-00-00,E124-00-00_0006       ,4147.4
    1300    1300
River Rch & RM=E124-00-00,E124-00-00_0006       ,3631
    1420    1420
River Rch & RM=E124-00-00,E124-00-00_0006       ,3120.7
    1550    1550
River Rch & RM=E124-00-00,E124-00-00_0006       ,2579.6
    1700    1700
River Rch & RM=E124-00-00,E124-00-00_0006       ,1895.1
    1840    1840
River Rch & RM=E124-00-00,E124-00-00_0006       ,1278.3
    2000    2000
River Rch & RM=E124-00-00,E124-00-00_0006       ,636.0
    2178    2178
Boundary for River Rch & Prof#=E124-00-00,E124-00-00_0006       , 1
Up Type= 0
Dn Type= 3
Dn Slope=.00093
Boundary for River Rch & Prof#=E124-00-00,E124-00-00_0006       , 2
Up Type= 0
Dn Type= 3
Dn Slope=.00093
DSS Import GetInterval= 0
DSS Import GetPeak= 0
DSS Import FillOption= 0

--- E124-00-00.f01 (steady flow) ---

Flow Title=FEMA Effective June 2007
Version=Version 3.0.1  Mar 2001
Number of Profiles= 4
Profile Names=10PCT_10yr, 2PCT_50yr, 1PCT_100yr, 0.2PCT_500yr
River Rch & RM=E124-00-00,E124-00-00_0006       ,7001.6
     620     870    1000    1410
River Rch & RM=E124-00-00,E124-00-00_0006       ,6264.7
     680     960    1100    1600
River Rch & RM=E124-00-00,E124-00-00_0006       ,5521.5
     710    1030    1160    1650
River Rch & RM=E124-00-00,E124-00-00_0006       ,4898.7
     750    1130    1240    1710
River Rch & RM=E124-00-00,E124-00-00_0006       ,4147.4
     780    1200    1300    1750
River Rch & RM=E124-00-00,E124-00-00_0006       ,3631.0
     850    1250    1420    1890
River Rch & RM=E124-00-00,E124-00-00_0006       ,3120.7
     920    1300    1550    2050
River Rch & RM=E124-00-00,E124-00-00_0006       ,2579.6
    1020    1440    1700    2260
River Rch & RM=E124-00-00,E124-00-00_0006       ,1895.1
    1110    1570    1840    2460
River Rch & RM=E124-00-00,E124-00-00_0006       ,1278.3
    1220    1730    2000    2690
River Rch & RM=E124-00-00,E124-00-00_0006       ,636.0
    1339    1894    2178    2946
Boundary for River Rch & Prof#=E124-00-00,E124-00-00_0006       , 1
Up Type= 0
Dn Type= 3
Dn Slope=.00093
Boundary for River Rch & Prof#=E124-00-00,E124-00-00_0006       , 2
Up Type= 0
Dn Type= 3
Dn Slope=.00093
Boundary for River Rch & Prof#=E124-00-00,E124-00-00_0006       , 3
Up Type= 0
Dn Type= 3
Dn Slope=.00093
Boundary for River Rch & Prof#=E124-00-00,E124-00-00_0006       , 4
Up Type= 0
Dn Type= 3
Dn Slope=.00093
DSS Import GetInterval= 0
DSS Import GetPeak= 0
DSS Import FillOption= 0

--- E124-00-00.f04 (steady flow) ---

Flow Title= Storage Routing
Version=Version 3.0.1  Mar 2001
Number of Profiles= 7
Profile Names=0.25x10% flood,0.50x10% flood,10% flood,2% flood,1% flood,0.2% flood,1.25x0.2% flood
River Rch & RM=E124-00-00,E124-00-00_0006       ,7001.6
     100     200     390     510     580     720     900
River Rch & RM=E124-00-00,E124-00-00_0006       ,6264.7
     110     220     440     590     660     820    1000
River Rch & RM=E124-00-00,E124-00-00_0006       ,5445.7
     130     250     490     650     730     900    1100
River Rch & RM=E124-00-00,E124-00-00_0006       ,4147.4
     150     290     570     760     850    1060    1300
River Rch & RM=E124-00-00,E124-00-00_0006       ,3631
     170     340     670     890    1000    1240    1600
River Rch & RM=E124-00-00,E124-00-00_0006       ,1895.1
     220     440     880    1170    1310    1630    2000
Boundary for River Rch & Prof#=E124-00-00,E124-00-00_0006       , 1
Up Type= 0
Dn Type= 3
Dn Slope=.00093
Boundary for River Rch & Prof#=E124-00-00,E124-00-00_0006       , 2
Up Type= 0
Dn Type= 3
Dn Slope=.00093
Boundary for River Rch & Prof#=E124-00-00,E124-00-00_0006       , 3
Up Type= 0
Dn Type= 3
Dn Slope=.00093
Boundary for River Rch & Prof#=E124-00-00,E124-00-00_0006       , 4
Up Type= 0
Dn Type= 3
Dn Slope=.00093
Boundary for River Rch & Prof#=E124-00-00,E124-00-00_0006       , 5
Up Type= 0
Dn Type= 3
Dn Slope=.00093
Boundary for River Rch & Prof#=E124-00-00,E124-00-00_0006       , 6
Up Type= 0
Dn Type= 3
Dn Slope=.00093
Boundary for River Rch & Prof#=E124-00-00,E124-00-00_0006       , 7
Up Type= 0
Dn Type= 3
Dn Slope=.00093
DSS Import GetInterval= 0
DSS Import GetPeak= 0
DSS Import FillOption= 0

--- E124-00-00.g01 (geometry) ---

Geom Title=E124-00-00 June 2007
Program Version=3.13

River Reach=E124-00-00      ,E124-00-00_0006
Reach XY= 30
      3069264.99       13896199.      3069431.25       13891608.
      3069465.25       13891018.        3069513.       13889763.
      3069548.75       13888251.       3069616.5       13887563.
       3069663.5       13887417.      3069694.25       13886856.
      3069763.11     13886777.94      3069858.59     13886709.36
      3070144.18     13886560.05      3070343.09     13886401.27
      3070810.85     13886119.08      3070836.89      13886088.7
      3070890.71     13886010.57      3070937.59     13885902.07
      3070984.46     13885056.58      3071009.64     13884999.29
      3071153.73     13884868.21      3071205.82     13884840.44
      3071318.66     13884823.94      3072292.62     13884876.89
      3073158.75       13884900.       3073273.5       13884872.
      3073319.68     13884835.53      3073341.41     13884794.23
      3073355.45     13884656.69      3073416.21     13882861.55
      3073394.51     13882739.16      3073333.75      13882618.5

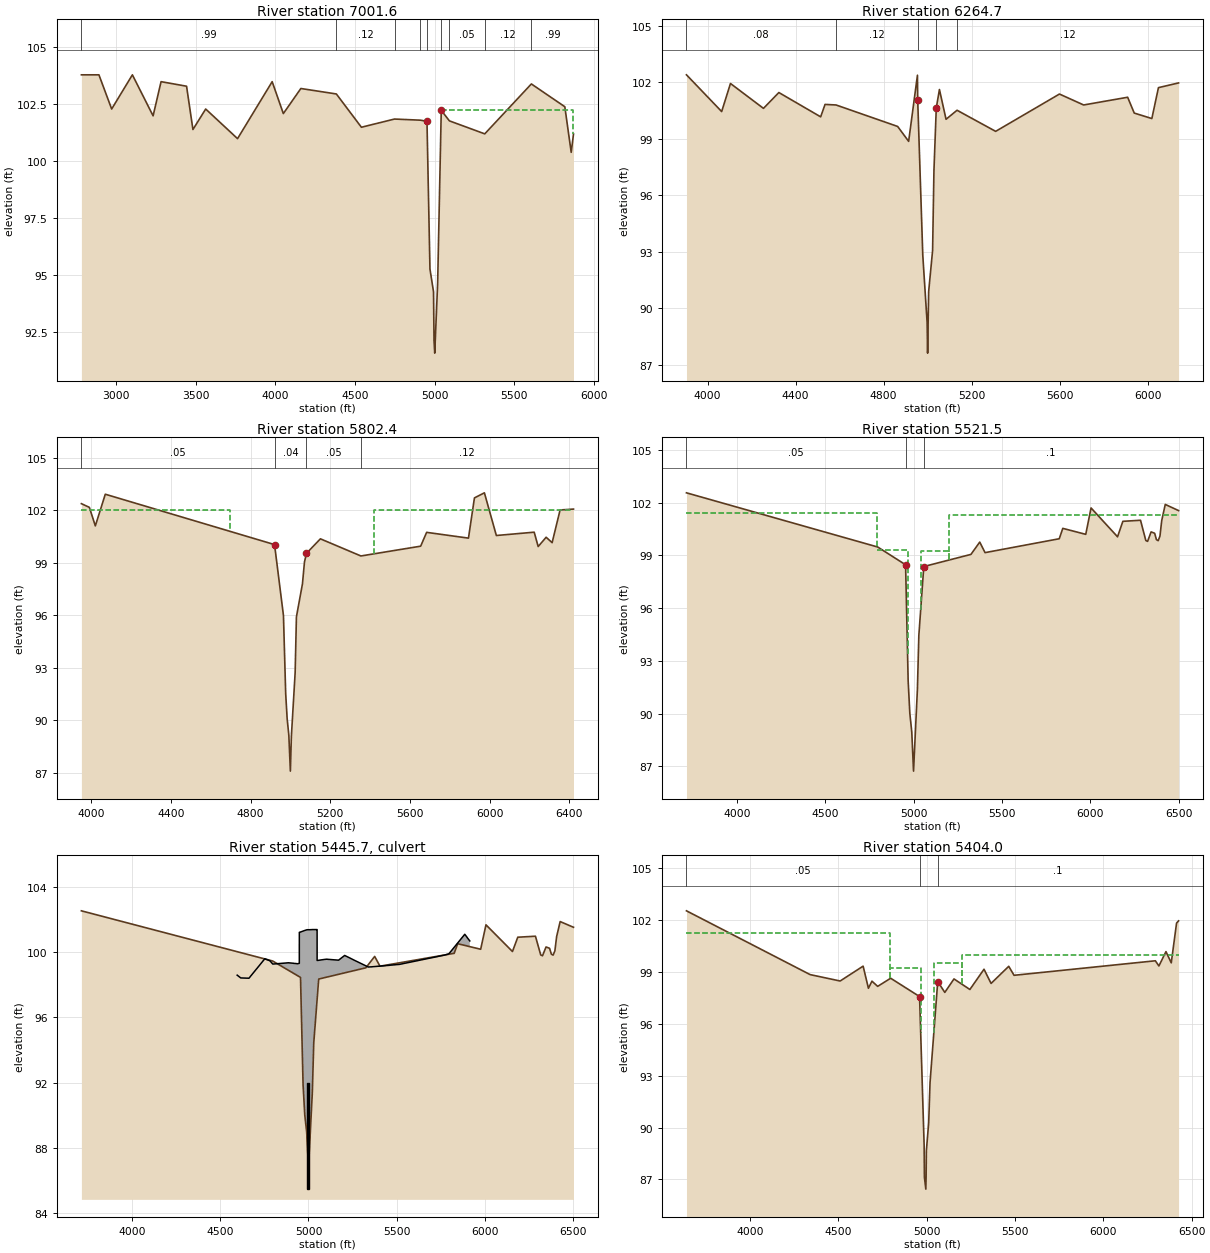
Type RM Length L Ch R = 1 ,7001.6  ,737.3,736.9,731.9
BEGIN DESCRIPTION:
Cross Section x09
Located At: FAIRBANKS-N HOUSTON
END DESCRIPTION:
XS GIS Cut Line= 4
      3070821.92      13888719.5      3070381.97     13887758.11
      3069687.81     13886580.93      3069030.23     13886485.57
#Sta/Elev= 30
  2783.5   103.8  2893.5   103.8  2973.5   102.3  3103.5   103.8  3233.5     102
  3283.5   103.5  3443.5   103.3  3483.5   101.4  3563.5   102.3  3763.5     101
  3980.8   103.5  4050.8   102.1  4160.8   103.2  4383.6  102.96  4540.8   101.5
  4748.5  101.86  4911.1  101.81  4952.3  101.76    4971   95.28  4993.4   94.28
  4996.6   92.13    5001   91.59  5019.2   94.64  5041.9  102.24  5093.1  101.78
  5314.9  101.21  5607.4   103.4  5817.4   102.4  5857.4   100.4  5871.8   101.2
#Mann= 9 ,-1 , 0
  2783.5     .99       0  4383.6     .12       0  4748.5     .05       0
  4911.1     .04       0  4952.3     .04       0  5041.9     .04       0
  5093.1     .05       0  5314.9     .12       0  5607.4     .99       0
#XS Ineff= 2 , 0
       0  4952.3  101.76  5041.9       0  102.24
Permanent Ineff=
       T       T
Bank Sta=4952.3,5041.9
Exp/Cntr=0.3,0.1

Type RM Length L Ch R = 1 ,6264.7  ,476.7,462.3,453
BEGIN DESCRIPTION:
Cross Section x08
END DESCRIPTION:
XS GIS Cut Line= 3
      3071028.11     13887271.62       3070237.2     13886109.66
      3069429.31     13885912.95
#Sta/Elev= 30
  3903.8  102.39  4063.8  100.44  4103.8  101.93  4253.8  100.61  4323.8  101.45
  4513.8  100.16  4533.8  100.82  4583.8  100.79  4863.8   99.65  4913.8   98.86
  4953.8  102.37  4954.9  101.08  4978.1   92.81  4997.8   89.24    5000   87.62
  5004.8   90.89  5022.7   93.07  5028.8    97.3  5039.4  100.63  5053.8  101.61
  5083.8  100.03  5133.8  100.51  5309.4   99.39  5599.4  101.37  5709.4  100.79
  5909.4   101.2  5939.4  100.36  6019.4  100.07  6049.4  101.71  6140.9  101.96
#Mann= 5 ,-1 , 0
  3903.8     .08       0  4583.8     .12       0  4954.9     .04       0
  5039.4     .05       0  5133.8     .12       0
#XS Ineff= 2 , 0
       0  4954.9  101.08  5039.4       0  100.63
Permanent Ineff=
       T       F
Bank Sta=4954.9,5039.4
Exp/Cntr=0.3,0.1

Type RM Length L Ch R = 1 ,5802.4  ,358.6,280.9,237.4
BEGIN DESCRIPTION:
Warren Road - 4
Interpolated channel, LIDAR overbanks
END DESCRIPTION:
XS GIS Cut Line= 4
      3071141.63     13887104.43       3070885.8     13886210.31
       3070686.1     13885995.55      3069446.33     13885858.49
#Sta/Elev= 30
  3950.8  102.38  3990.8  102.17  4020.8  101.11  4070.8  102.92 4920.52  100.04
 4965.24   95.99 4976.44   91.53 4983.78   90.09 4992.28   89.14    5000   87.09
 5005.06   89.09 5023.93   92.71 5030.36   95.91  5060.7    97.8  5070.7   99.04
  5080.7   99.54  5150.8  100.37  5354.1   99.39  5654.1   99.95  5684.1  100.74
  5894.1  100.41  5924.1  102.71  5974.1     103  6034.1  100.56  6224.1  100.75
  6244.1   99.93  6284.1  100.46  6314.1  100.15  6354.1  102.02  6421.4  102.07
#Mann= 4 ,-1 , 0
  3950.8     .05       0 4920.52     .04       0  5080.7     .05       0
  5354.1     .12       0
#XS Ineff= 2 ,-1
  3950.8 4694.36     102 5422.11  6421.4     102
Permanent Ineff=
       F       F
Bank Sta=4920.52,5080.7
Exp/Cntr=0.5,0.3

Type RM Length L Ch R = 1 ,5521.5  ,101.1,117.5,106.6
BEGIN DESCRIPTION:
Warren Road - 3
END DESCRIPTION:
XS GIS Cut Line= 4
      3071247.11     13886950.36      3071143.46     13885873.02
      3070815.83     13885861.95      3069442.23      13885791.6
#Sta/Elev= 30
  3714.7  102.55  4797.1   99.47    4955   98.46  4969.5   91.86    4979   90.02
    4990   88.95    5000   86.73    5022   91.41    5030   94.44    5058   98.36
  5324.9   99.05  5374.8   99.75  5404.8   99.15  5824.8   99.94  5844.8  100.53
  5974.8  100.19  6004.8  101.69  6154.8  100.05  6184.8  100.93  6284.8  100.99
  6314.8   99.84  6324.8   99.79  6344.8  100.33  6364.8  100.25  6374.8   99.89
  6384.8   99.83  6394.8  100.09  6404.8  100.97  6424.8  101.89  6500.2  101.54
#Mann= 3 ,-1 , 0
  3714.7     .05       0    4955     .04       0    5058      .1       0
#XS Ineff= 4 ,-1
  3714.7 4794.36  101.39 4794.36 4966.15   99.28  5040.4    5200   99.23
    5200  6500.2  101.31
Permanent Ineff=
       F       F       F       F
Bank Sta=4955,5058
Exp/Cntr=0.5,0.3

Type RM Length L Ch R = 2 ,5445.7  ,,,
BEGIN DESCRIPTION:
WARREN ROAD
Structure ID: E124-00-00-02
END DESCRIPTION:
Bridge Culvert--1,0,-1,-1, 0
Deck Dist Width WeirC Skew NumUp NumDn MinLoCord MaxHiCord MaxSubmerge Is_Ogee
34,63.5,2.6,0, 51, 55, , , 0.95, 0, ,,,
  4596.5  4616.5  4663.1  4676.5  4716.5  4753.1  4756.5    4782  4798.1  4886.9
  4915.1  4918.1  4923.4    4939 4948.19  4948.3 4948.41  4955.2  4980.2  4992.2
  4993.7  4995.8  4997.5  5003.4  5004.1  5005.8  5006.8  5023.9  5036.9  5045.8
 5048.79  5048.9 5049.01  5056.9  5074.2  5101.3  5170.4  5204.9  5238.8  5258.8
  5338.8  5354.8  5454.8  5461.3  5514.8  5769.5  5794.8  5884.8  5898.2  5898.3
  5913.3
    98.6   98.43   98.41   98.59   99.12   99.61   99.59   99.48   99.28   99.36
   99.33   99.32   99.32    99.3   99.33  101.23  101.23  101.25  101.35  101.39
  101.39  101.39  101.39  101.39  101.39  101.39  101.39   101.4   101.4   101.4
   101.4   101.4    99.5   99.51   99.54   99.58   99.52   99.81   99.63   99.52
    99.1   99.11    99.2   99.21   99.26   99.83   99.91  101.11  100.92  100.91
   100.7
                                                                                
                                                                                
                                                                                
                                                                                
                                                                                
        
  4393.1  4396.5  4421.5  4539.4  4596.5  4616.5  4663.1  4676.5  4716.5  4753.1
  4756.5    4782  4798.1  4886.9  4915.1  4918.1  4923.4    4939 4948.19  4948.3
 4948.41  4955.2  4980.2  4992.2  4993.7  4995.8  4997.5  5003.4  5004.1  5005.8
  5006.8  5023.9  5036.9  5045.8 5048.79  5048.9 5049.01  5056.9  5074.2  5101.3
  5170.4  5204.9  5238.8  5258.8  5338.8  5354.8  5454.8  5461.3  5514.8  5769.5
  5794.8  5884.8  5898.2  5898.3  5913.3
   98.55   98.51    98.5   98.54    98.6   98.43   98.41   98.59   99.12   99.61
   99.59   99.48   99.28   99.36   99.33   99.32   99.32    99.3   99.33  101.23
  101.23  101.25  101.35  101.39  101.39  101.39  101.39  101.39  101.39  101.39
  101.39   101.4   101.4   101.4   101.4   101.4    99.5   99.51   99.54   99.58
   99.52   99.81   99.63   99.52    99.1   99.11    99.2   99.21   99.26   99.83
   99.91  101.11  100.92  100.91   100.7
                                                                                
                                                                                
                                                                                
                                                                                
                                                                                
                                        
BR Coef= 1 , 0 , 0 ,1.25, 0 ,,,0.8,-1,2,0,
WSPro=,,,, 1 ,,,, 0 ,,,, 0 ,,,,-1 ,-1 ,-1 , 0 , 0 , 0 , 0 , 0
Culvert=2,6.5,6,63.5,0.012,0.5,1,8,2,85.46,4993.8,85.17,4993.8,Culvert #1  , 0 ,34
Culvert Bottom n=0.012
Culvert=2,6.5,6,63.5,0.012,0.5,1,8,2,85.48,5002.8,85.18,5002.8,Culvert #2  , 0 ,34
Culvert Bottom n=0.012
BC Design=,, 0 ,, 0 ,,,,,,
BC HTab HWMax=101.26

Type RM Length L Ch R = 1 ,5404.0  ,100.1,91.8,91.4
BEGIN DESCRIPTION:
Warren Road - 2
END DESCRIPTION:
XS GIS Cut Line= 4
      3071325.29      13886863.5      3071221.89     13885786.04
      3070820.24      13885768.8       3069520.4     13885704.74
#Sta/Elev= 30
  3640.3  102.54  4340.3   98.85  4510.3   98.48  4640.3   99.34  4670.3   98.06
  4690.3   98.47  4722.7   98.17  4796.3   98.64  4959.9   97.58  4985.8   88.95
  4987.2   87.14  4995.3   86.44  4996.9   87.15  4998.3   88.66  5011.5   90.28
  5019.1    92.6  5062.7   98.45  5102.7   97.82  5154.7    98.6  5244.7   97.99
  5324.7   99.16  5364.7   98.34  5464.7   99.33  5494.7   98.81  6294.7   99.65
  6314.7   99.35  6354.7  100.18  6384.7   99.53  6414.7  101.83  6426.1  101.96
#Mann= 3 ,-1 , 0
  3640.3     .05       0  4959.9     .04       0  5062.7      .1       0
#XS Ineff= 4 ,-1
  3640.3 4794.36  101.26 4794.36 4966.15   99.26  5040.4    5200    99.5
    5200  6426.1     100
Permanent Ineff=
       F       F       F       F
Bank Sta=4959.9,5062.7
Exp/Cntr=0.5,0.3

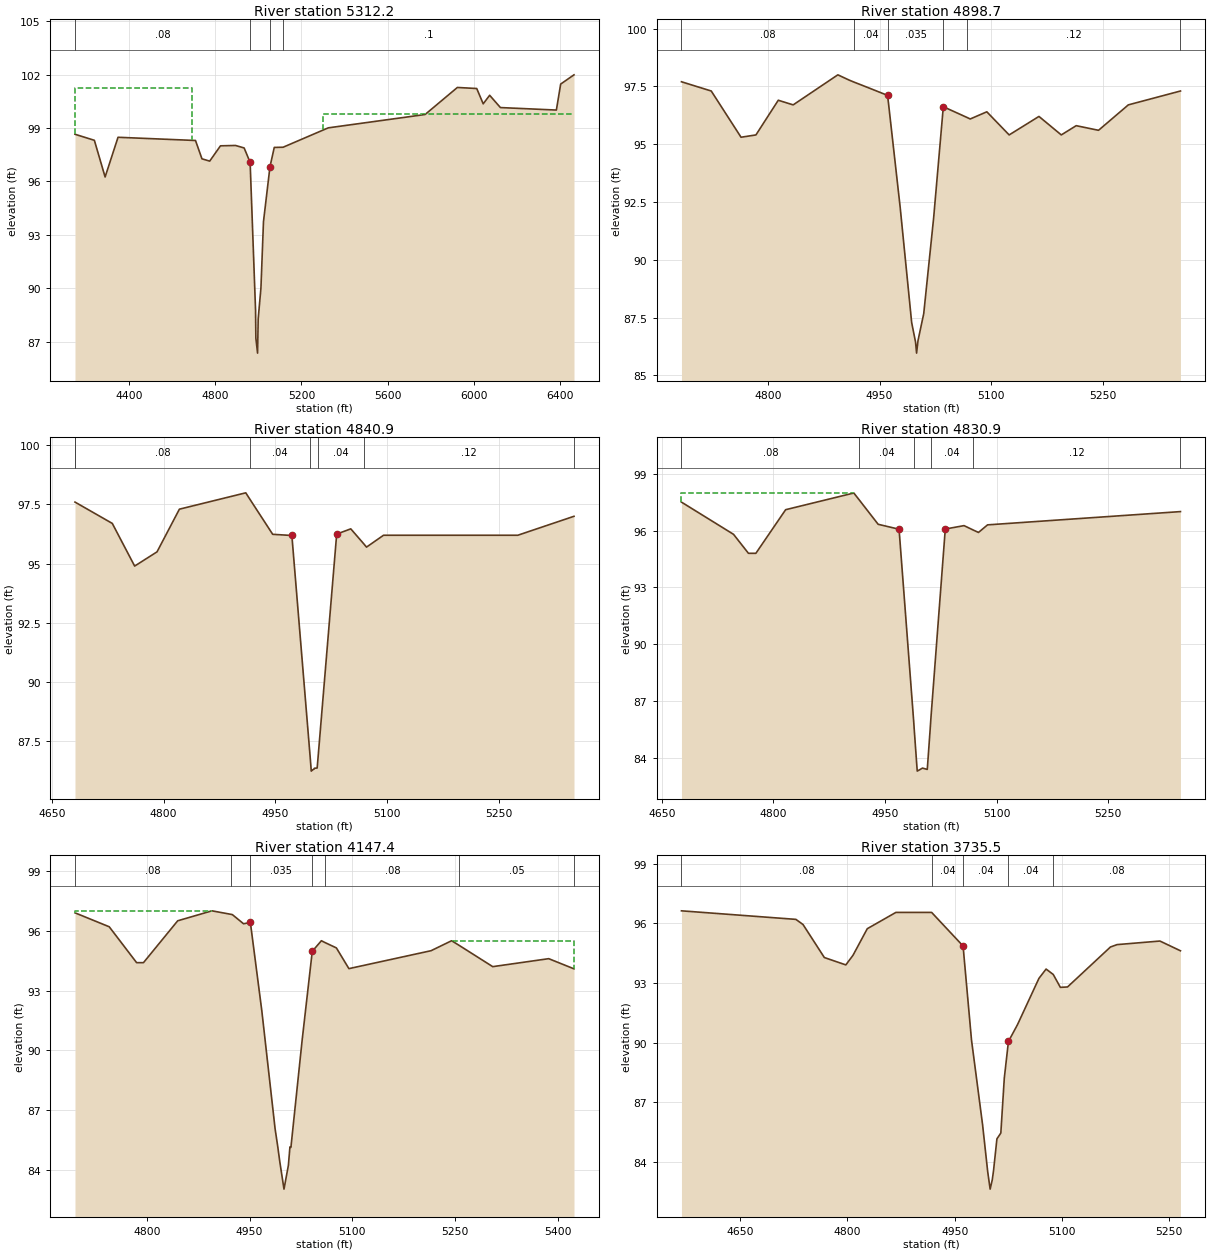
Type RM Length L Ch R = 1 ,5312.2  ,412.2,413.5,415.5
BEGIN DESCRIPTION:
Warren Road - 1
Interpolated channel, LIDAR overbanks
END DESCRIPTION:
XS GIS Cut Line= 4
       3071800.4     13885729.86      3071176.36     13885680.78
      3070835.67     13885669.27      3069486.06     13885590.16
#Sta/Elev= 30
  4147.7   98.65  4237.7   98.31  4287.7   96.25  4347.7   98.48  4707.7    98.3
  4737.7   97.27  4773.7   97.14  4823.7      98  4893.7   98.02  4933.7   97.88
 4961.55   97.07 4986.83   88.74 4988.19   87.19  4996.1   86.35 4998.99   88.28
 5011.72      90 5023.59   93.74  5053.7   96.82  5073.7   97.91  5114.6   97.92
  5324.6   99.01  5774.6   99.76  5924.6  101.28  6014.6  101.22  6044.6  100.36
  6074.6  100.84  6124.6  100.15  6384.6  100.01  6404.6  101.47  6466.5  101.99
#Mann= 4 ,-1 , 0
  4147.7     .08       0 4961.55     .04       0  5053.7     .06       0
  5114.6      .1       0
#XS Ineff= 2 ,-1
  4147.7 4689.81  101.26 5299.27  6466.5   99.77
Permanent Ineff=
       F       F
Bank Sta=4961.55,5053.7
Exp/Cntr=0.3,0.1

Type RM Length L Ch R = 1 ,4898.7  ,60.1,57.8,55.3
BEGIN DESCRIPTION:
Cross Section x07
Located At: DS WARREN
END DESCRIPTION:
XS GIS Cut Line= 2
      3071285.78     13885291.67      3070619.13     13885224.44
#Sta/Elev= 29
    4684    97.7    4724    97.3    4764    95.3    4784    95.4    4814    96.9
    4834    96.7    4894      98  4909.3   97.77  4916.1   97.68  4935.1   97.44
  4960.8   97.11  4977.7   92.26  4993.1   87.28  4998.3   86.44  4999.7   85.96
  5001.6    86.5  5009.3   87.67  5022.6   91.81  5035.6   96.62  5067.8   96.15
  5071.7   96.09    5094    96.4    5124    95.4    5164    96.2    5194    95.4
    5214    95.8    5244    95.6    5284    96.7    5354    97.3
#Mann= 6 ,-1 , 0
    4684     .08       0  4916.1     .04       0  4960.8    .035       0
  5035.6     .04       0  5067.8     .12       0    5354      .2       0
Bank Sta=4960.8,5035.6
Exp/Cntr=0.3,0.1

Type RM Length L Ch R = 1 ,4840.9  ,9.5,10,10.5
BEGIN DESCRIPTION:
Cross Section E124-00-00-X6B
END DESCRIPTION:
XS GIS Cut Line= 4
      3071292.61     13885205.56      3071065.36     13885202.23
      3070878.89     13885202.23      3070624.17     13885183.92
#Sta/Elev= 24
  4681.2    97.6  4731.2    96.7  4761.2    94.9  4791.2    95.5  4821.2    97.3
  4910.2   97.99  4915.5   97.73  4946.3   96.24    4972   96.19  4996.6   86.82
  4997.7   86.38    4998   86.25  4999.7    86.3  5001.9   86.34  5002.2   86.37
  5005.9   86.38    5007   86.78  5032.1   96.25    5051   96.47  5068.4   95.84
  5072.1    95.7  5094.9    96.2  5274.9    96.2  5350.3      97
#Mann= 7 , 1 , 0
  4681.2      .2       0  4681.2     .08       0  4915.5     .04       0
  4996.6     .03       0    5007     .04       0  5068.4     .12       0
  5350.3      .2       0
Bank Sta=4972,5032.1
Exp/Cntr=0.3,0.1

Type RM Length L Ch R = 1 ,4830.9  ,619.5,683.5,736.1
BEGIN DESCRIPTION:
Cross Section E124-00-00-X6A
END DESCRIPTION:
XS GIS Cut Line= 4
      3071297.61     13885188.08      3071065.36     13885192.24
      3070886.39     13885192.24      3070628.33     13885167.27
#Sta/Elev= 22
  4676.5    97.5  4746.5    95.8  4766.5    94.8  4776.5    94.8  4816.5    97.1
  4908.1   97.98  4915.3   97.62  4940.8   96.33  4968.9   96.07  4988.5   85.96
  4989.2   85.55  4993.3   83.31  5000.4   83.47  5006.8    83.4  5010.7   85.53
  5011.8   86.16    5031   96.08  5056.2   96.26  5068.4   96.03  5075.6    95.9
  5087.8    96.3    5347      97
#Mann= 6 ,-1 , 0
  4676.5     .08       0  4915.3     .04       0  4988.5     .03       0
  5011.8     .04       0  5068.4     .12       0    5347      .2       0
#XS Ineff= 2 , 0
         4908.04   97.99
Permanent Ineff=
       F       F
Bank Sta=4968.9,5031
Exp/Cntr=0.3,0.1

Type RM Length L Ch R = 1 ,4147.4  ,409.5,411.9,409.8
BEGIN DESCRIPTION:
Cross Section x06
Located At: US WOODLAND
END DESCRIPTION:
XS GIS Cut Line= 3
      3071425.84     13885140.41      3071443.89     13884479.97
      3071440.47     13884412.03
#Sta/Elev= 30
  4695.1    96.9  4745.1    96.2  4785.1    94.4  4795.1    94.4  4845.1    96.5
  4895.1      97  4923.5   96.82  4924.9   96.81  4941.3   96.35  4951.2   96.42
  4967.9   91.99  4987.3   86.07    4991   85.22  4994.2   84.41  5000.3   83.04
  5006.7   84.23    5009   85.16  5010.4   85.13  5026.8   90.51  5041.6   94.97
  5054.9    95.5  5060.7    95.4  5076.8   95.14  5095.1    94.1  5215.1      95
  5245.1    95.5  5256.4   95.26  5305.1    94.2  5386.9    94.6 5423.79   94.09
#Mann= 7 ,-1 , 0
  4695.1     .08       0  4923.5     .04       0  4951.2    .035       0
  5041.6     .04       0  5060.7     .08       0  5256.4     .05       0
 5423.79      .2       0
#XS Ineff= 2 , 0
       0 4895.07      97  5245.1       0    95.5
Permanent Ineff=
       F       T
Bank Sta=4951.2,5041.6
Exp/Cntr=0.3,0.1

Type RM Length L Ch R = 1 ,3735.5  ,100,104.5,100.1
BEGIN DESCRIPTION:
Woodland West Drive - 4
Interpolated channel, LIDAR overbanks
END DESCRIPTION:
XS GIS Cut Line= 4
      3071800.86      13885280.1      3071836.16     13885093.59
      3071848.92     13884674.64      3071811.37     13884594.29
#Sta/Elev= 30
  4567.9   96.63  4727.9    96.2  4737.9   95.94  4767.7   94.28  4797.7   93.91
  4807.7   94.39  4827.7   95.73  4867.7   96.55  4917.7   96.55 4961.65   94.86
 4973.44   90.13  4988.9   85.88 4996.04   83.52  4999.5   82.63 5002.43   83.09
 5004.15   83.53 5008.99   85.16 5014.44   85.45 5019.28   88.21 5025.08   90.06
  5037.7    90.9  5067.7   93.23  5077.7    93.7  5087.7   93.43  5097.7   92.78
  5107.7    92.8  5167.7   94.81  5176.9   94.93  5236.9   95.11  5265.6   94.62
#Mann= 5 ,-1 , 0
  4567.9     .08       0  4917.7     .04       0 4961.65     .04       0
 5025.08     .04       0  5087.7     .08       0
#XS Ineff= 2 , 0
       0  4867.7   96.55               0
Permanent Ineff=
       F       F
Bank Sta=4961.65,5025.08
Exp/Cntr=0.5,0.3

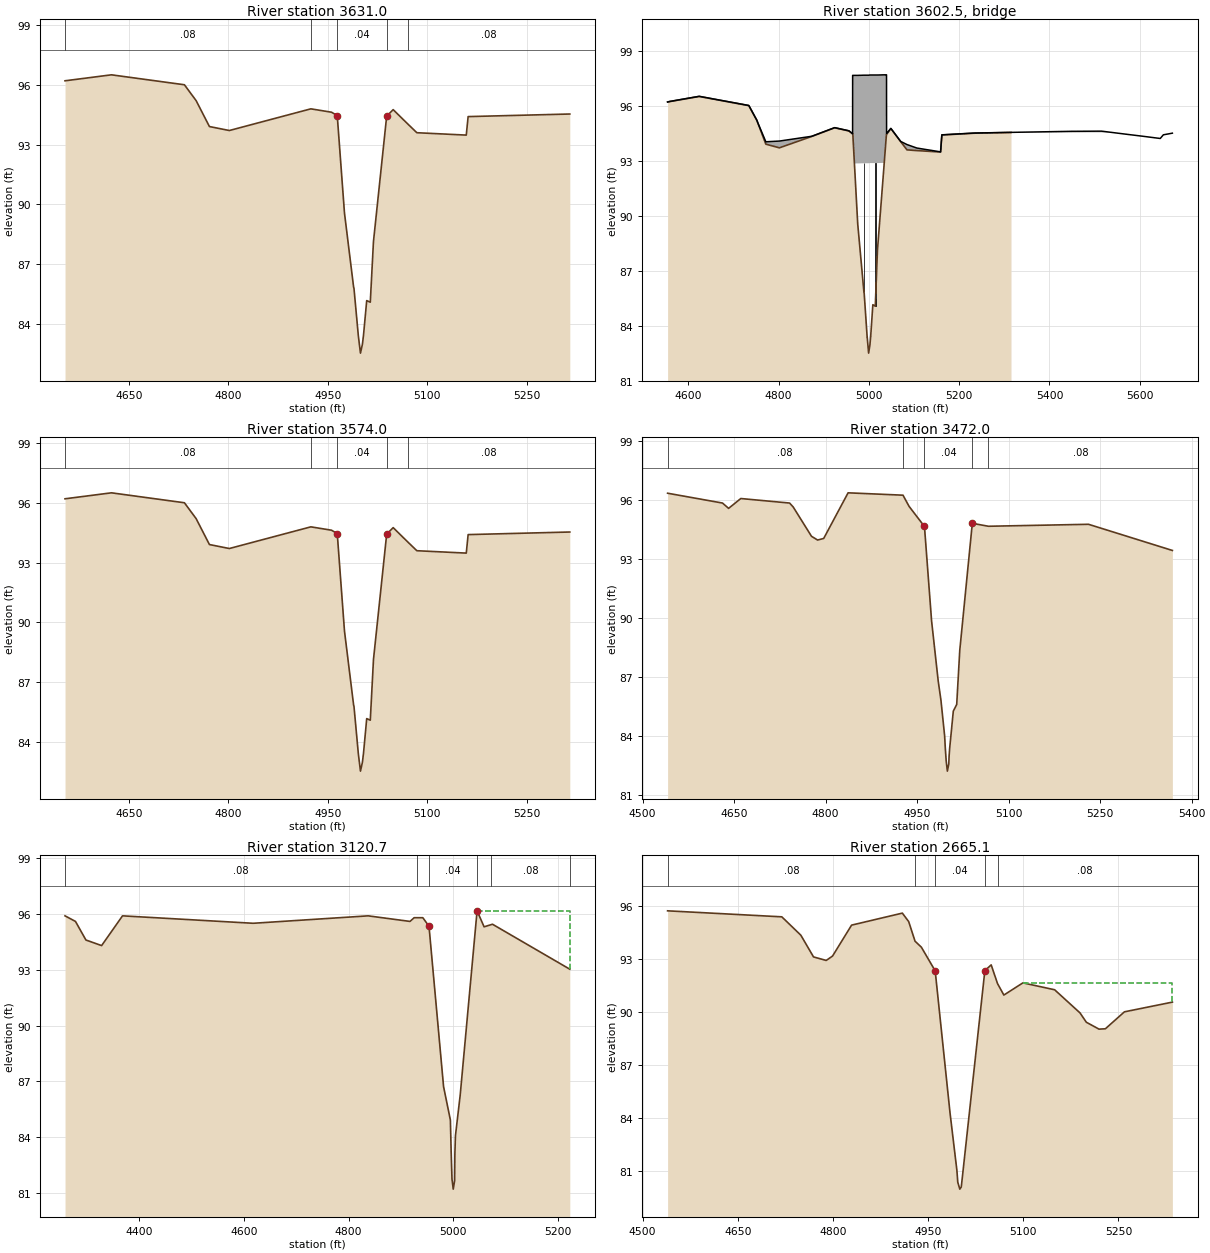
Type RM Length L Ch R = 1 ,3631.0  ,56.8,57,63.1
BEGIN DESCRIPTION:
Woodland West Drive - 3
END DESCRIPTION:
XS GIS Cut Line= 4
      3071899.11     13885298.71      3071935.87     13885104.48
      3071949.59     13884653.88      3071901.97     13884551.95
#Sta/Elev= 26
  4553.9   96.21  4623.9   96.51  4733.9   96.01  4751.6   95.21  4771.6   93.91
  4801.6   93.71  4924.5    94.8  4955.7   94.63  4964.3   94.46  4975.2   89.56
    4989   85.83  4989.5   85.78  4996.1   83.39  4999.3   82.52  5002.2   82.96
 5003.91   83.43  5008.7   85.16  5014.1   85.08  5018.9   88.13  5038.8   94.43
  5048.6   94.76  5070.3   94.05  5084.3    93.6  5158.8   93.48  5161.6   94.41
  5314.9   94.54
#Mann= 5 ,-1 , 0
  4553.9     .08       0  4924.5     .04       0  4964.3     .04       0
  5038.8     .04       0  5070.3     .08       0
#XS Ineff= 2 , 0
       0    4954   94.02    5048       0   93.48
Permanent Ineff=
       T       T
Bank Sta=4964.3,5038.8
Exp/Cntr=0.5,0.3

Type RM Length L Ch R = 3 ,3602.5  ,,,
BEGIN DESCRIPTION:
WOODLAND WEST DRIVE
Structure ID: E124-00-00-01
END DESCRIPTION:
Bridge Culvert--1,0,-1,-1, 0
Deck Dist Width WeirC Skew NumUp NumDn MinLoCord MaxHiCord MaxSubmerge Is_Ogee
10,37,2.6,0, 54, 54, , , 0.95, 0, ,,,
  4553.9  4558.6  4623.9  4733.9  4751.6  4753.6  4771.6  4801.6  4873.3  4923.8
  4924.5  4928.2  4955.7 4963.79  4963.9 4964.01  4964.1  4964.3 4968.21  4968.3
  4975.2    4989  4989.5  4996.1 4996.21  4999.3  5002.2  5003.8 5003.91  5008.7
  5014.1  5018.9 5033.19  5033.3  5038.8 5038.89    5039 5039.11  5048.6    5052
  5070.3  5084.3  5106.1  5158.8  5161.6  5235.5  5237.5  5447.5  5515.5  5567.5
  5607.5  5645.5  5652.4  5672.4
    96.2   96.23   96.51   96.01   95.21   95.08   94.03   94.07   94.33    94.8
    94.8   94.78   94.63   94.47   97.65   97.65   97.65   97.65   97.65   97.65
   97.65   97.66   97.66   97.66   97.66   97.66   97.67   97.67   97.67   97.67
   97.67   97.67   97.68   97.68   97.68   97.68   97.68   94.48   94.76   94.65
   94.05   93.88   93.69   93.48   94.41   94.51   94.51    94.6   94.61   94.45
   94.33   94.21   94.41    94.5
                                                                                
                                                           94.45   92.69   92.85
   92.85   92.86   92.86   92.86   92.86   92.86   92.87   92.87   92.87   92.87
   92.87   92.87   92.88   92.68   94.42
                                                                                
                                
  4553.9  4558.6  4623.9  4733.9  4751.6  4753.6  4771.6  4801.6  4873.3  4923.8
  4924.5  4928.2  4955.7 4963.79  4963.9 4964.01  4964.1  4964.3 4968.21  4968.3
  4975.2    4989  4989.5  4996.1 4996.21  4999.3  5002.2  5003.8 5003.91  5008.7
  5014.1  5018.9 5033.19  5033.3  5038.8 5038.89    5039 5039.11  5048.6    5052
  5070.3  5084.3  5106.1  5158.8  5161.6  5235.5  5237.5  5447.5  5515.5  5567.5
  5607.5  5645.5  5652.4  5672.4
    96.2   96.23   96.51   96.01   95.21   95.08   94.03   94.07   94.33    94.8
    94.8   94.78   94.63   94.47   97.65   97.65   97.65   97.65   97.65   97.65
   97.65   97.66   97.66   97.66   97.66   97.66   97.67   97.67   97.67   97.67
   97.67   97.67   97.68   97.68   97.68   97.68   97.68   94.48   94.76   94.65
   94.05   93.88   93.69   93.48   94.41   94.51   94.51    94.6   94.61   94.45
   94.33   94.21   94.41    94.5
                                                                                
                                                           94.45   92.69   92.85
   92.85   92.86   92.86   92.86   92.86   92.86   92.87   92.87   92.87   92.87
   92.87   92.87   92.88   92.68   94.42
                                                                                
                                
Pier Skew, UpSta & Num, DnSta & Num=  ,4989, 2 ,4989, 2 , 0 , 0 , 0 ,,
     1.2     1.2
   84.73   93.86
     1.2     1.2
   85.25   94.38
Pier Skew, UpSta & Num, DnSta & Num=  ,5014.1, 2 ,5014.1, 2 , 0 , 0 , 0 ,,
     1.2     1.2
   84.08   93.87
     1.2     1.2
    84.6   94.39
BR Coef= 1 , 1 , 0 ,1.25, 0 ,,,0.8,0,2,0,
WSPro=,,,, 1 ,,,, 0 ,,,, 0 ,,,,-1 ,-1 ,-1 , 0 , 0 , 0 , 0 , 0
BR U #Sta/Elev= 48
  4553.9    96.2  4558.6   96.22  4623.9    96.5  4733.9      96  4751.6    95.2
  4753.6   95.07  4771.6    93.9  4801.6    93.7  4873.3   94.32  4923.8   94.79
  4924.5   94.79  4928.2   94.77  4955.7   94.62 4963.79   94.46  4963.9   94.46
 4964.01   94.46  4964.1   94.45  4964.3   94.45 4968.21   92.69  4968.3   92.65
  4975.2   89.55    4989   85.82  4989.5   85.77  4996.1   83.38 4996.21   83.38
  4999.3   82.51  5002.2   82.95  5003.8   83.42 5003.91   83.42  5008.7   85.15
  5014.1   85.07  5018.9   88.12 5033.19   92.64  5033.3   92.68  5038.8   94.42
 5038.89   94.42    5039   94.43 5039.11   94.43  5048.6   94.75    5052   94.64
  5070.3   94.04  5084.3   93.59  5106.1   93.55  5158.8   93.47  5161.6    94.4
  5235.5    94.5  5237.5    94.5  5314.9   94.54
BR U #Mann= 6
  4553.9      .2  4558.6     .08  4924.5     .04  4964.3     .04  5038.8     .04
  5070.3     .08
BR U Banks=4964.3,5038.8
BR D #Sta/Elev= 48
  4553.9    96.2  4558.6   96.22  4623.9    96.5  4733.9      96  4751.6    95.2
  4753.6   95.07  4771.6    93.9  4801.6    93.7  4873.3   94.32  4923.8   94.79
  4924.5   94.79  4928.2   94.77  4955.7   94.62 4963.79   94.46  4963.9   94.46
 4964.01   94.46  4964.1   94.45  4964.3   94.45 4968.21   92.69  4968.3   92.65
  4975.2   89.55    4989   85.82  4989.5   85.77  4996.1   83.38 4996.21   83.38
  4999.3   82.51  5002.2   82.95  5003.8   83.42 5003.91   83.42  5008.7   85.15
  5014.1   85.07  5018.9   88.12 5033.19   92.64  5033.3   92.68  5038.8   94.42
 5038.89   94.42    5039   94.43 5039.11   94.43  5048.6   94.75    5052   94.64
  5070.3   94.04  5084.3   93.59  5106.1   93.55  5158.8   93.47  5161.6    94.4
  5235.5    94.5  5237.5    94.5  5314.9   94.54
BR D #Mann= 6
  4553.9      .2  4558.6     .08  4924.5     .04  4964.3     .04  5038.8     .04
  5070.3     .08
BR D Banks=4964.3,5038.8
BC Design=,, 0 ,, 0 ,,,,,,
BC HTab HWMax=96.51

Type RM Length L Ch R = 1 ,3574.0  ,100,102,100.1
BEGIN DESCRIPTION:
Woodland West Drive - 2
END DESCRIPTION:
XS GIS Cut Line= 4
      3071961.95     13885302.18      3071998.79     13885107.57
      3072012.56     13884655.39      3071964.43     13884552.38
#Sta/Elev= 26
  4553.9   96.21  4623.9   96.51  4733.9   96.01  4751.6   95.21  4771.6   93.91
  4801.6   93.71  4924.5    94.8  4955.7   94.63  4964.3   94.46  4975.2   89.56
    4989   85.83  4989.5   85.78  4996.1   83.39  4999.3   82.52  5002.2   82.96
 5003.91   83.43  5008.7   85.16  5014.1   85.08  5018.9   88.13  5038.8   94.43
  5048.6   94.76  5070.3   94.05  5084.3    93.6  5158.8   93.48  5161.6   94.41
 5314.89   94.54
#Mann= 5 ,-1 , 0
  4553.9     .08       0  4924.5     .04       0  4964.3     .04       0
  5038.8     .04       0  5070.3     .08       0
#XS Ineff= 2 , 0
       0    4954   94.02    5048       0   93.48
Permanent Ineff=
       T       T
Bank Sta=4964.3,5038.8
Exp/Cntr=0.5,0.3

Type RM Length L Ch R = 1 ,3472.0  ,351.1,351.3,353.9
BEGIN DESCRIPTION:
Woodland West Drive - 1
Interpolated channel, LIDAR overbanks
END DESCRIPTION:
XS GIS Cut Line= 4
      3072060.21      13885320.7       3072098.5     13885118.46
      3072113.24     13884634.63      3072055.03     13884510.05
#Sta/Elev= 30
  4540.9   96.35  4630.9   95.85  4640.9   95.58  4660.9   96.08  4740.9   95.85
  4746.8   95.65  4776.8   94.16  4786.8   93.97  4796.8   94.05  4836.8   96.37
  4926.8   96.25  4936.8   95.68 4961.98   94.66 4973.68   89.85 4984.57   86.79
 4989.03   85.82 4995.09      84 4996.11   83.41  4997.6   82.74 4999.55   82.22
 5001.88   82.59 5002.33   82.96 5003.31   83.38 5009.27   85.27 5014.86   85.61
 5019.83   88.35 5040.42   94.82  5066.8   94.67  5230.9   94.77  5368.4   93.44
#Mann= 5 ,-1 , 0
  4540.9     .08       0  4926.8     .04       0 4961.98     .04       0
 5040.42     .04       0  5066.8     .08       0
Bank Sta=4961.98,5040.42
Exp/Cntr=0.3,0.1

Type RM Length L Ch R = 1 ,3120.7  ,454.2,455.6,452.5
BEGIN DESCRIPTION:
Cross Section x05
Located At: DS WOODLAND
END DESCRIPTION:
XS GIS Cut Line= 2
      3072434.89     13885621.91      3072467.07     13884656.66
#Sta/Elev= 26
  4257.6    95.9  4277.6    95.6  4297.6    94.6  4327.6    94.3  4367.6    95.9
  4617.6    95.5  4837.6    95.9  4917.6    95.6  4925.6    95.8  4930.2    95.8
  4942.2    95.8    4954   95.34  4981.9   86.71  4994.9   84.92  4996.5   83.11
    4998   81.74  5000.4    81.2    5003   81.65  5003.5   83.08  5004.6   84.07
  5013.7   86.26    5046   96.17  5059.4   95.31  5073.3   95.43  5075.4   95.45
 5223.42   93.03
#Mann= 6 ,-1 , 0
  4257.6     .08       0  4930.2     .04       0    4954     .04       0
    5046     .04       0  5073.3     .08       0 5223.42      .2       0
#XS Ineff= 2 , 0
       0                    5046       0   96.17
Permanent Ineff=
       F       T
Bank Sta=4954,5046
Exp/Cntr=0.3,0.1

Type RM Length L Ch R = 1 ,2665.1  ,85,85.5,86
BEGIN DESCRIPTION:
Interpolated channel, LIDAR overbanks
END DESCRIPTION:
XS GIS Cut Line= 2
       3072909.5      13885355.7      3072915.13     13884560.25
#Sta/Elev= 30
  4539.4   95.73  4719.4   95.39  4749.4   94.35  4769.4   93.12  4789.4   92.92
  4799.4   93.17  4829.4   94.92  4909.4    95.6  4919.4   95.12  4929.4   94.01
  4939.4   93.67 4961.16   92.33  4984.5    84.3 4995.38   81.03 4996.76   80.36
 4999.98   79.97 5002.23   80.09 5003.38   80.45 5039.43   92.34  5049.4   92.67
  5059.4   91.61  5069.4   90.96  5099.4   91.65  5149.4   91.26  5189.4   89.95
  5199.4   89.42  5219.4   89.03  5229.4   89.05  5259.4   90.01    5335   90.56
#Mann= 5 ,-1 , 0
  4539.4     .08       0  4929.4     .05       0 4961.16     .04       0
 5039.43     .05       0  5059.4     .08       0
#XS Ineff= 2 , 0
       0                  5099.4       0   91.65
Permanent Ineff=
       F       F
Bank Sta=4961.16,5039.43
Exp/Cntr=0.3,0.1