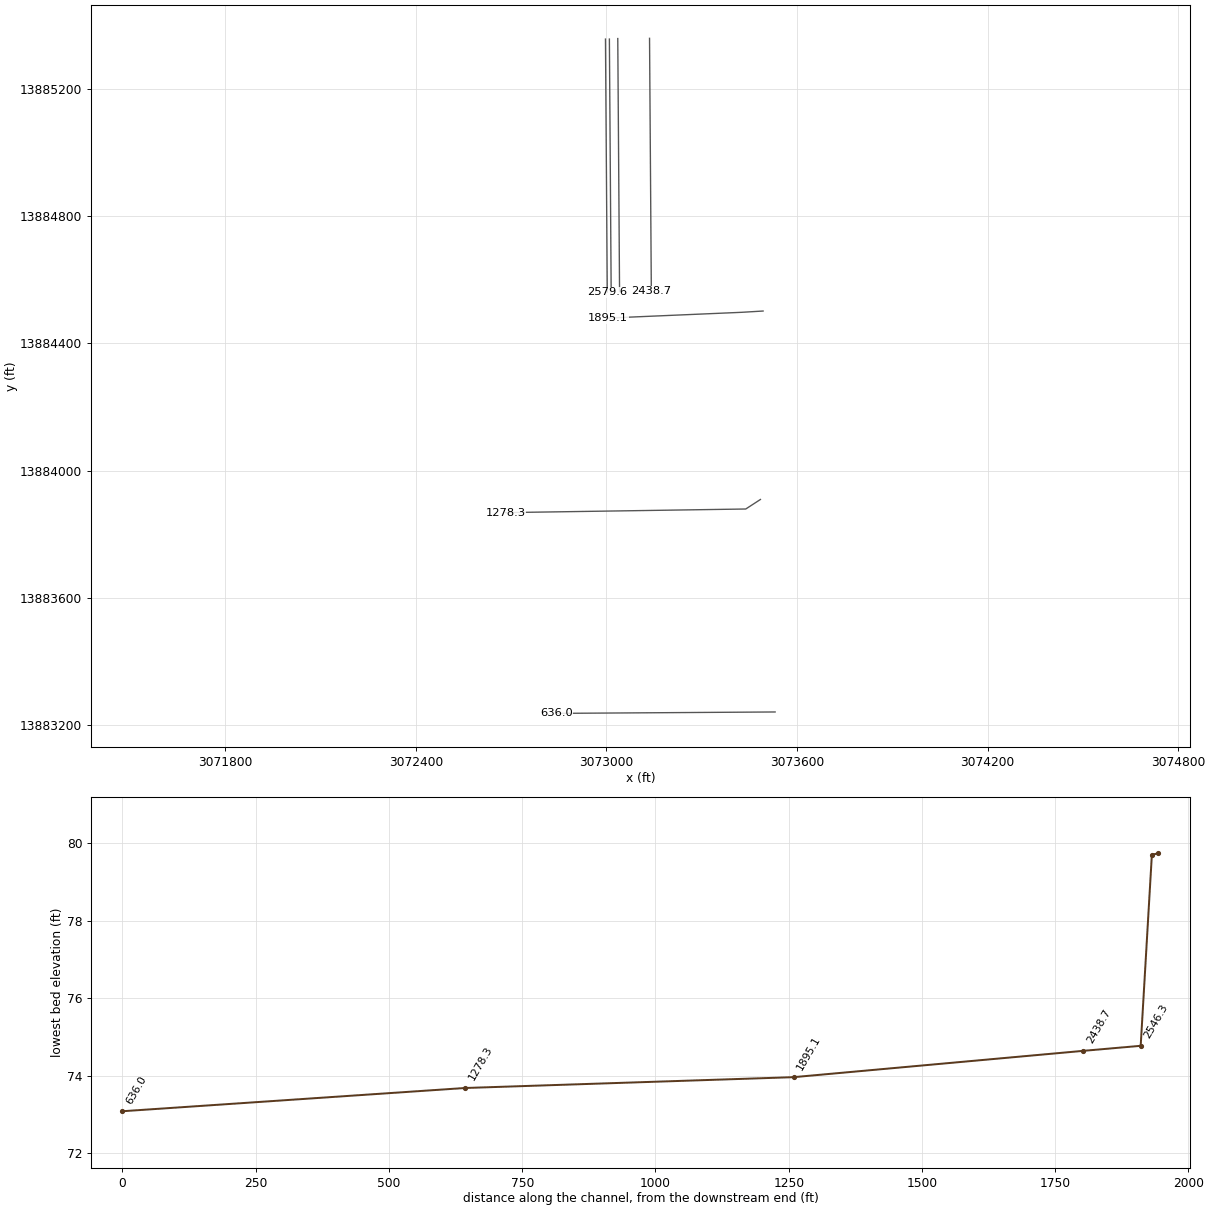
HEC-RAS study E124-00-00.prj: E124-00-00

--- E124-00-00.g01 (geometry) --- (continued)

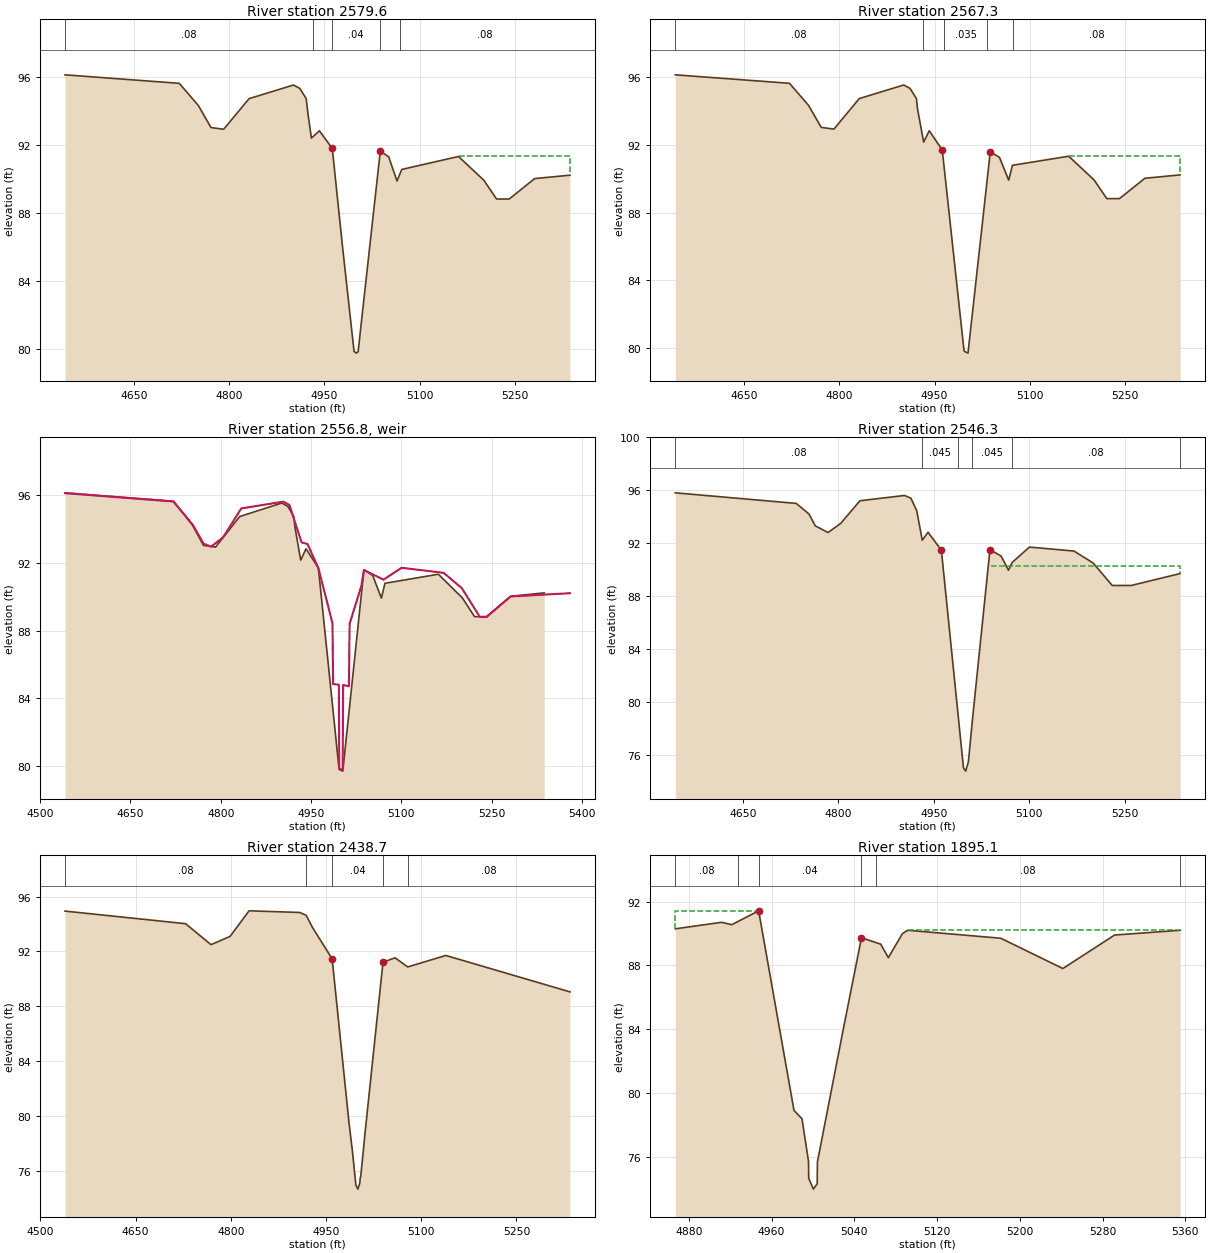
Type RM Length L Ch R = 1 ,2579.6  ,12.5,12.3,12
BEGIN DESCRIPTION:
S1B - 4
Cross Section x04
Located At: N. SHADYVALE
END DESCRIPTION:
XS GIS Cut Line= 2
      3072997.19      13885356.4      3073002.82      13884560.9
#Sta/Elev= 29
  4541.4    96.1  4721.4    95.6  4751.4    94.3  4771.4      93  4791.4    92.9
  4831.4    94.7  4901.4    95.5  4911.4    95.3  4921.4    94.7    4924   93.86
  4929.6   92.38    4932   92.46  4942.2   92.81  4962.5   91.77  4978.8   85.94
  4996.8   79.85  4999.9   79.74  5003.2   79.82  5038.2   91.62  5051.4   91.28
  5064.5   89.86  5068.7   90.24  5072.1   90.54  5161.4    91.3  5201.4    89.9
  5221.4    88.8  5241.4    88.8  5281.4      90    5337    90.2
#Mann= 5 ,-1 , 0
  4541.4     .08       0    4932     .05       0  4962.5     .04       0
  5038.2     .05       0  5068.7     .08       0
#XS Ineff= 2 , 0
       0                  5161.4       0    91.3
Permanent Ineff=
       F       F
Bank Sta=4962.5,5038.2
Exp/Cntr=0.7,0.5

Type RM Length L Ch R = 1 ,2567.3  ,20,21,22
BEGIN DESCRIPTION:
S1B - 3
END DESCRIPTION:
XS GIS Cut Line= 2
       3073009.5     13885356.49      3073015.12     13884560.95
#Sta/Elev= 30
  4541.4   96.12  4721.4   95.62  4751.4   94.32  4771.4   93.02  4791.4   92.92
  4831.4   94.72  4901.4   95.52  4911.4   95.32  4921.4   94.72  4923.2    94.1
    4932   92.31  4932.8   92.15  4941.6   92.82  4962.1   91.69  4965.1   90.66
  4996.3   79.89  4997.1   79.81  5002.7   79.71  5033.4    90.1  5037.8   91.58
  5052.3   91.25  5066.8   89.91  5072.7   90.79  5073.4   90.79  5161.4   91.32
  5201.4   89.92  5221.4   88.82  5241.4   88.82  5281.4   90.02    5337   90.22
#Mann= 5 ,-1 , 0
  4541.4     .08       0    4932    .045       0  4965.1    .035       0
  5033.4    .045       0  5073.4     .08       0
#XS Ineff= 3 ,-1
    4900    4961    90.3    5040  5161.4    90.3  5161.4    5337   91.32
Permanent Ineff=
       F       F       F
Bank Sta=4962.1,5037.8
Exp/Cntr=0.7,0.5

Type RM Length L Ch R = 5 ,2556.8  ,,,
BEGIN DESCRIPTION:
WEIR IMMEDIATELY DS OF X04
Structure ID: E124-00-00-S1B
END DESCRIPTION:
IW Pilot Flow=0
#Inline Weir SE= 30
  4541.4    96.1  4721.4   95.61  4754.1    94.2  4771.4   93.12  4784.1   92.95
  4804.1    93.5  4834.1    95.2  4904.1    95.6  4914.1    95.4  4934.1    93.2
  4944.1    93.1  4962.1   91.68  4985.5   88.44  4986.6   84.84  4996.1   84.81
  4996.8   79.83  5002.5   79.81  5003.2   84.79  5012.9   84.71    5014    88.4
  5033.4   90.61  5037.8   91.57  5070.3      91  5100.3    91.7  5170.3    91.4
  5200.3    90.5  5230.3    88.8  5241.4    88.8  5281.4   90.01  5379.9    90.2
IW Dist,WD,Coef,Skew,MaxSub,Min_El,Is_Ogee,SpillHt,DesHd
10,1,3,0,0.95,, 0 ,,,0.1,0.1,

Type RM Length L Ch R = 1 ,2546.3  ,100.2,107.6,100.5
BEGIN DESCRIPTION:
S1B - 2
Cross Section FIELD_DS
Located At: WEIR IMMEDIATELY DS OF X04
END DESCRIPTION:
XS GIS Cut Line= 2
      3073035.88     13885358.11      3073041.51     13884562.57
#Sta/Elev= 28
  4544.1    95.8  4734.1      95  4754.1    94.2  4764.1    93.3  4784.1    92.8
  4804.1    93.5  4834.1    95.2  4904.1    95.6  4914.1    95.4  4923.3   94.45
    4932   92.22  4941.1   92.82    4962   91.47  4988.7   78.81  4996.7   75.02
  5000.2   74.77  5004.5   75.49  5010.8   78.65  5038.3    91.5  5055.9   91.02
  5067.4   89.95  5073.4   90.55  5100.3    91.7  5170.3    91.4  5200.3    90.5
  5230.3    88.8  5260.3    88.8 5337.02    89.7
#Mann= 6 ,-1 , 0
  4544.1     .08       0    4932    .045       0  4988.7    .035       0
  5010.8    .045       0  5073.4     .08       0 5337.02      .2       0
#XS Ineff= 2 , 0
       0    4961    90.3    5040       0    90.3
Permanent Ineff=
       F       F
Bank Sta=4962,5038.3
Exp/Cntr=0.7,0.5

Type RM Length L Ch R = 1 ,2438.7  ,610.5,543.6,484.1
BEGIN DESCRIPTION:
S1B - 1
Interpolated channel, LIDAR overbanks
END DESCRIPTION:
XS GIS Cut Line= 2
      3073135.88      13885358.8      3073141.51     13884563.28
#Sta/Elev= 28
  4538.7   94.95  4728.7   94.03  4768.7    92.5  4798.7    93.1  4828.7   94.97
  4908.7   94.85  4918.7   94.64  4928.7   93.75  4959.6   91.46 4985.87   79.62
    4988   78.79 4989.17   78.32 4991.78   77.32 4996.51   75.14 4996.62   75.13
 4996.78   74.94 5000.23   74.64 5003.38   75.12 5003.54   75.36 5004.69   75.59
 5010.49   78.28 5011.22   78.65 5024.44   84.48 5039.72   91.21  5058.7   91.54
  5078.7   90.87  5138.7   91.71  5334.3   89.05
#Mann= 5 ,-1 , 0
  4538.7     .08       0  4918.7     .05       0  4959.6     .04       0
 5039.72     .05       0  5078.7     .08       0
Bank Sta=4959.6,5039.72
Exp/Cntr=0.3,0.1

Type RM Length L Ch R = 1 ,1895.1  ,618.1,616.8,615.8
BEGIN DESCRIPTION:
Cross Section x03
Located At: W BATTLECREEK
END DESCRIPTION:
XS GIS Cut Line= 3
      3073493.32     13884501.48      3073426.08     13884497.45
      3073005.63     13884479.36
#Sta/Elev= 24
 4866.88   90.29  4911.6    90.7  4921.5   90.55  4927.5   90.75  4937.4   91.08
  4947.5   91.42  4981.7   78.89  4989.4   78.38  4995.7    75.7  4995.9   74.64
  5000.4   73.96  5004.1    74.3  5004.3   75.66  5028.9   83.85  5046.9   89.73
  5060.9   89.43  5065.5   89.33  5072.9   88.48  5086.5   89.99  5091.6    90.2
  5181.6    89.7  5241.6    87.8  5291.6    89.9    5355    90.2
#Mann= 6 ,-1 , 0
 4866.88     .08       0  4927.5     .05       0  4947.5     .04       0
  5046.9     .05       0  5060.9     .08       0    5355      .2       0
#XS Ineff= 2 , 0
       0  4947.5   91.42 5091.59       0   90.21
Permanent Ineff=
       T       F
Bank Sta=4947.5,5046.9
Exp/Cntr=0.3,0.1

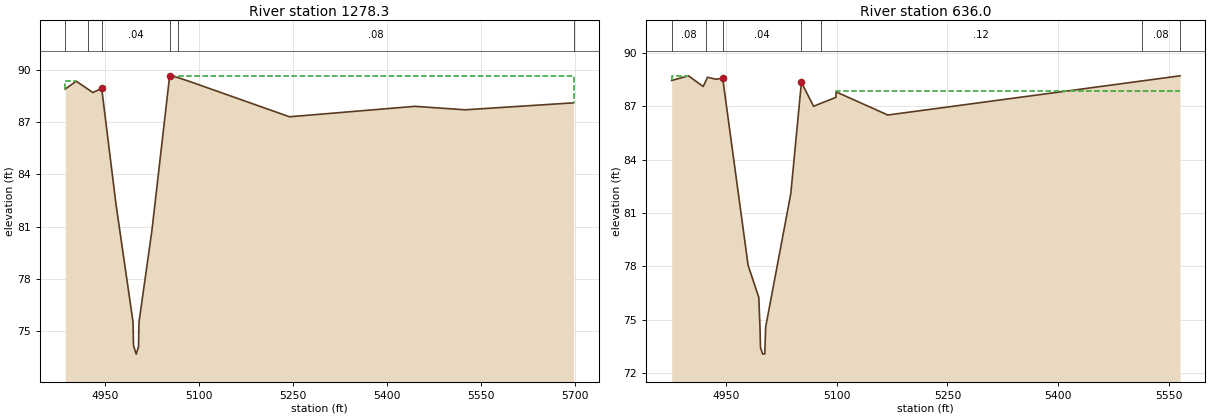
Type RM Length L Ch R = 1 ,1278.3  ,635,642.3,640
BEGIN DESCRIPTION:
Cross Section x02
Located At: SW SALGE RD
END DESCRIPTION:
XS GIS Cut Line= 3
      3073484.92     13883909.02       3073438.7     13883879.05
       3072683.5      13883867.7
#Sta/Elev= 20
 4887.03   88.89  4904.6   89.34  4922.7    88.9  4931.1   88.69  4945.2   88.93
    4968   82.29  4995.2   75.52  4995.9   74.18  5000.3   73.68    5004   74.11
  5004.7   75.51  5025.3   80.77  5053.6   89.65  5064.7   89.57  5067.6   89.54
  5085.9   89.32  5244.7    87.3  5444.7    87.9  5524.7    87.7  5697.7    88.1
#Mann= 6 ,-1 , 0
 4887.03      .1       0  4922.7     .05       0  4945.2     .04       0
  5053.6     .05       0  5067.6     .08       0  5697.7      .2       0
#XS Ineff= 2 , 0
       0  4904.6   89.34  5053.6       0   89.65
Permanent Ineff=
       T       F
Bank Sta=4945.2,5053.6
Exp/Cntr=0.3,0.1

Type RM Length L Ch R = 1 ,636.0   ,0,0,0
BEGIN DESCRIPTION:
Cross Section x01
Located At: WEST OF KELLWOOD
END DESCRIPTION:
XS GIS Cut Line= 2
      3073531.14     13883240.94      3072842.81     13883236.52
#Sta/Elev= 23
  4876.6   88.44  4899.3    88.7  4919.3    88.1  4922.9   88.42  4925.1   88.62
  4936.4   88.51  4945.7   88.56  4980.1   78.07  4994.6   76.26  4996.2   74.59
  4996.9   73.44  4999.9   73.08  5002.7   73.09  5003.9    74.6  5037.9   82.08
  5052.3   88.33  5068.8   86.99  5078.8   87.16    5099   87.49  5099.3    87.8
  5169.3    86.5  5513.1   88.41    5565    88.7
#Mann= 7 ,-1 , 0
  4876.6     .08       0  4922.9     .05       0  4945.7     .04       0
  5052.3     .05       0  5078.8     .12       0  5513.1     .08       0
    5565      .2       0
#XS Ineff= 2 , 0
       0  4899.3    88.7 5099.27       0   87.83
Permanent Ineff=
       T       F
Bank Sta=4945.7,5052.3
Exp/Cntr=0.3,0.1

Chan Stop Cuts=-1
Use User Specified Reach Order=0
User Specified Reach Order=E124-00-00      ,E124-00-00_0006